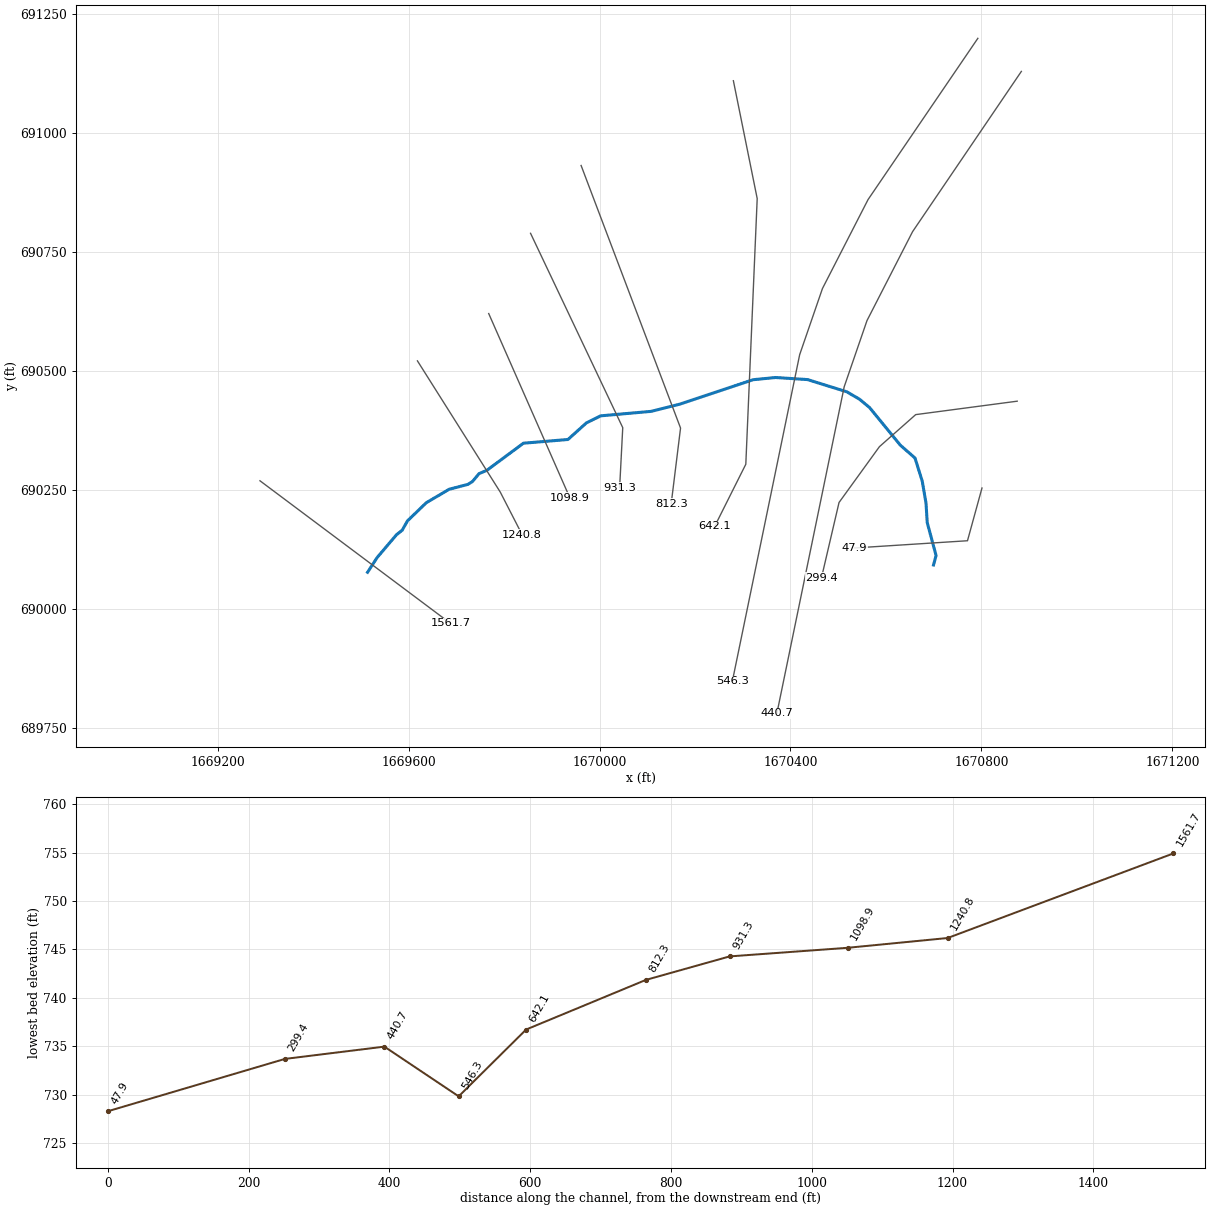
--- SPNGTNSRN.prj (project) ---

Proj Title=SPNGTNSRN
Current Plan=p01
Default Exp/Contr=0,0
English Units
Geom File=g01
Geom File=g09
Flow File=f01
Plan File=p01
BEGIN DESCRIPTION:
END DESCRIPTION:
DSS Export Rating Curves= 0
DSS Export Rating Curve Sorted= 0
DSS Export Volume Flow Curves= 0
DXF Filename=..\..\..\..\..\Engineering\Hydraulics\SPNGTNSRN\SPNGTNSRN.
DXF OffsetX= 0
DXF OffsetY= 0
DXF ScaleX= 0
DXF ScaleY= 0

--- SPNGTNSRN.p01 (plan) ---

Plan Title=Floodplain
Program Version=4.10
Short Identifier=Floodplain
Geom File=g01
Flow File=f01
Subcritical Flow
K Sum by GR= 0
Std Step Tol= 0.01
Critical Tol= 0.01
Num of Std Step Trials= 20
Max Error Tol= 0.3
Flow Tol Ratio= 0.001
Split Flow NTrial= 30
Split Flow Tol= 0.02
Split Flow Ratio= 0.02
Log Output Level= 0
Friction Slope Method= 1
Unsteady Friction Slope Method= 2
Unsteady Bridges Friction Slope Method= 1
Parabolic Critical Depth
Global Vel Dist= 0 , 0 , 0
Global Log Level= 0
CheckData=True
Encroach Param=-1 ,0,0, 0
Run HTab= 0
Run UNet= 0
Run PostProcess= 0
Run WQNet= 0
UNET Theta= 0
UNET Theta Warmup= 0
UNET ZTol= 0
UNET ZSATol= 0
UNET MxIter= 0
UNET MaxInSteps= 0
UNET DtIC= 0
UNET DtMin= 0
UNET MaxCRTS= 0
UNET WFStab= 0
UNET SFStab= 0
UNET WFX= 1
UNET SFX= 1
UNET DSS MLevel= 1
UNET DZMax Abort= 0
UNET Convert EG Bridges= 0
UNET Use Existing IB Tables= 0
UNET Froude Reduction=False
UNET Froude Limit= 0
UNET Froude Power= 0
UNET Time Slicing=0,0, 5
UNET Junction Losses=0
Write IC File= 0
Write IC File at Sim End=0
Echo Input=False
Echo Parameters=False
Echo Output=False
Write Detailed= 0
WQ AD Non Conservative
WQ ULTIMATE=-1
WQ Max Comp Step=1HOUR
WQ Output Interval=15MIN
WQ Output Selected Increments= 0
WQ Output face flow=0
WQ Output face velocity=0
WQ Output face area=0
WQ Output face dispersion=0
WQ Output cell volume=0
WQ Output cell surface area=0
WQ Output cell continuity=0
WQ Output cumulative cell continuity=0
WQ Output face conc=0
WQ Output face dconc_dx=0
WQ Output face courant=0
WQ Output face peclet=0
WQ Output face adv mass=0
WQ Output face disp mass=0
WQ Output cell mass=0
WQ Output cell source sink temp=0
WQ Output cell source sink nsm=0
WQ Output MaxMinRange=-1
WQ Daily Max Min Mean=-1
WQ Daily Range=0
WQ Daily Time=0
WQ Create Restart=0
WQ Fixed Restart=0
WQ System Summary=0
WQ Use Fixed Temperature=0
Sorting and Armoring Iterations= 10
XS Update Threshold= 0.02
Hydraulics Update Threshold= 0.02
Energy Slope Method= 1
Volume Change Method= 0
XS Weighting Method= 0
Number of US Weighted Cross Sections= 1
Number of DS Weighted Cross Sections= 1
Upstream XS Weight=0.25
Main XS Weight=0.5
Downstream XS Weight=0.25
Number of DS XS's Weighted with US Boundary= 1
Upstream Boundary Weight= 1
Weight of XSs Associated with US Boundary= 0
Number of US XS's Weighted with DS Boundary= 1
Downstream Boundary Weight= 0.5
Weight of XSs Associated with DS Boundary= 0.5
Sediment Output Level= 4
Mass or Volume Output= 0
Output Increment Type= 1
Profile and TS Output Increment= 10
XS Output Flag= 0
XS Output Increment= 10
Disregard all LS=0
Disregard all Conn=0
Disregard all Breaches=0
Disregard all Pumps=0

--- SPNGTNSRN.f01 (steady flow) ---

Flow Title=NFF Regression Equation
Program Version=4.00
Number of Profiles=1
Profile Names=P100yr
River Rch & RM=SPNGTNSRN,Main      ,1561.7
885.7168
River Rch & RM=SPNGTNSRN,Main      ,812.3
899.4251
Boundary for River Rch & Prof#=SPNGTNSRN,Main      ,1
Up Type=0
Dn Type=3
Dn Slope=0.013171

--- SPNGTNSRN.g01 (geometry) ---

Geom Title=2003 WV SAMB 3 Meter DEM
Program Version=4.10

River Reach=SPNGTNSRN       ,Main
Reach XY= 30
     1669514.036      690077.375     1669534.125      690108.392
      1669574.72       690156.25     1669586.595      690165.694
     1669597.498      690185.139     1669637.012      690223.333
     1669684.929      690251.597     1669724.234      690261.875
     1669733.818      690267.917     1669747.498      690284.375
     1669764.026      690291.459       1669840.6      690348.295
     1669933.832      690356.114     1669972.374      690390.836
     1670002.409      690405.766     1670108.138      690415.141
     1670168.554      690430.419     1670321.766      690481.634
     1670369.004      690486.199     1670435.625      690481.877
     1670518.294      690456.113      1670544.66       690440.55
     1670565.591      690423.198     1670630.143      690344.134
      1670660.85      690317.225     1670676.025      690268.569
     1670683.901      690222.675     1670686.458      690181.808
     1670705.001      690112.462     1670699.657      690092.646

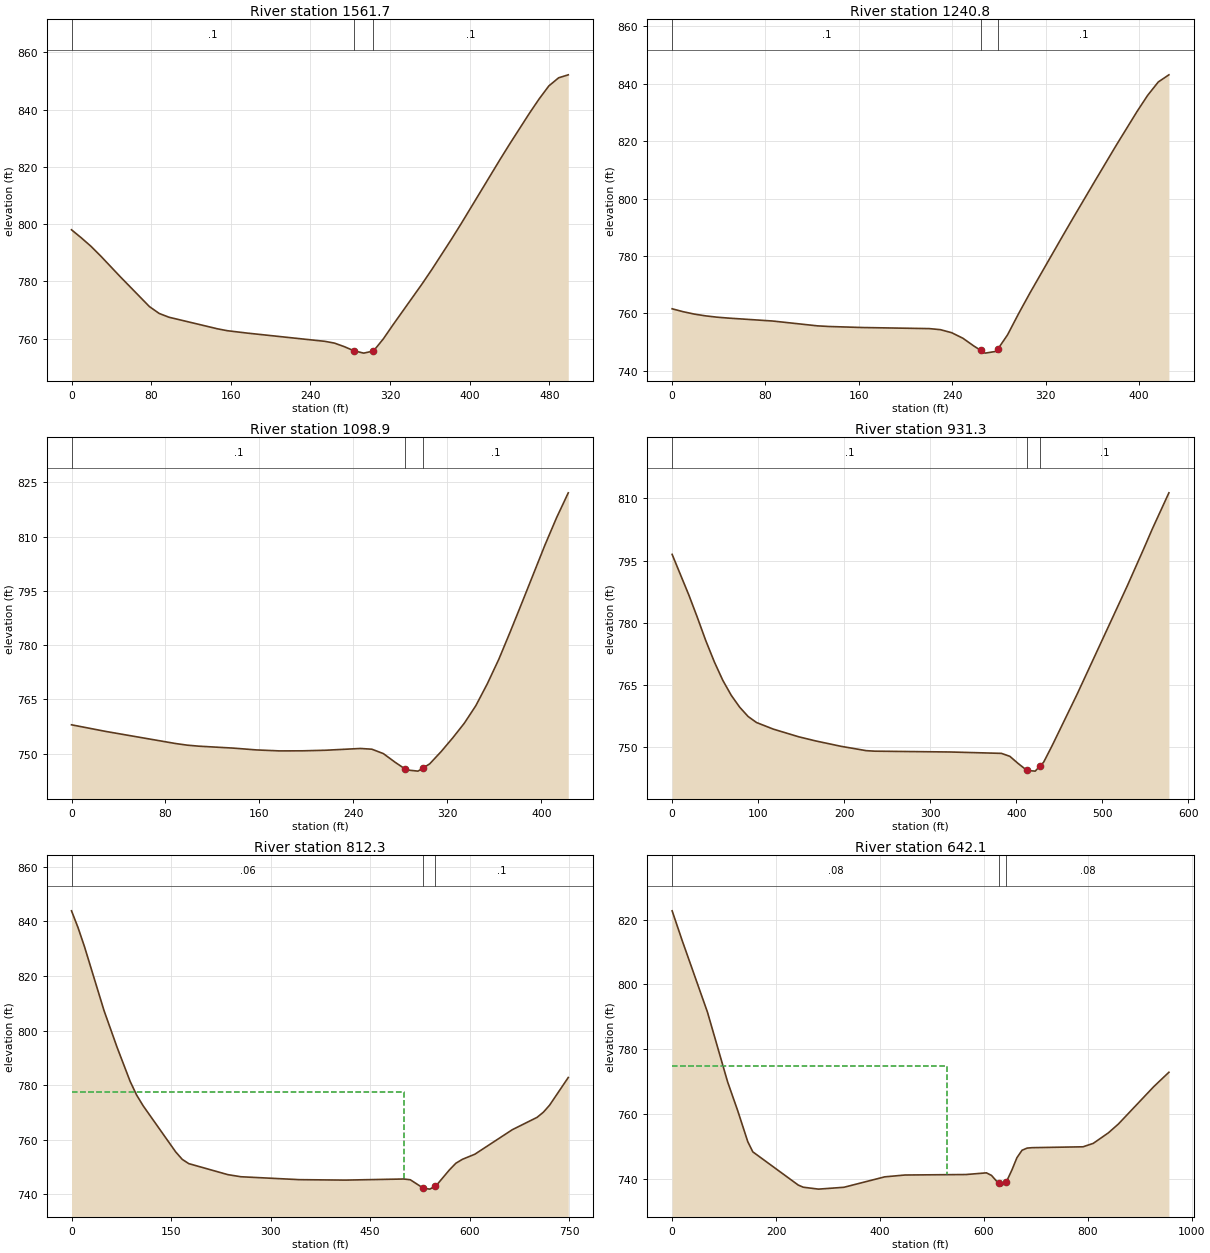
Type RM Length L Ch R = 1 ,1561.7  ,328.8,320.9,312
XS GIS Cut Line= 2
     1669288.611      690269.422     1669687.917      689969.943
#Sta/Elev= 30
       0  798.01     9.8  795.21    19.6  792.23    29.4  788.83    48.9  781.65
    78.3  771.18    88.1  768.79    97.9  767.47   146.8  763.41   156.6  762.76
   176.2  761.94   254.5  759.05   264.2  758.43     274   757.2   283.8  755.75
   293.6  754.93   303.4  755.68   313.2  759.86     323  764.81   352.3  779.14
   362.1  784.17   381.7   794.7   391.5  800.15   430.6  822.59   440.4  828.06
     460  838.67   469.8   843.7   479.6  848.26   489.4  851.09   499.1  852.13
#Mann= 3 , 0 , 0
       0      .1       0   283.8    .045       0   303.4      .1       0
Bank Sta=283.8,303.4
XS Rating Curve= 0 ,0
Exp/Cntr=0.3,0.1

Type RM Length L Ch R = 1 ,1240.8  ,144.8,141.9,138.4
XS GIS Cut Line= 3
     1669618.472      690521.158     1669792.083       690245.55
     1669837.656      690156.575
#Sta/Elev= 30
       0  761.62     9.6  760.59    19.2  759.76    28.7  759.16    38.3  758.71
    47.9  758.39    86.2  757.36   124.5  755.68   134.1  755.46   162.9   755.1
   220.4  754.72   229.9  754.35   239.5   753.3   249.1  751.38   258.7  748.62
   264.4  747.16   268.2  746.18   277.8   746.8   279.4  747.76   287.4  752.53
     297  760.01   306.6  767.12   334.8  787.09   343.9  793.45   362.1  805.99
   380.3   818.4   398.4  830.35   407.5  835.98   416.6  840.63   425.7  843.12
#Mann= 3 , 0 , 0
       0      .1       0   264.4    .045       0   279.4      .1       0
Bank Sta=264.4,279.4
XS Rating Curve= 0 ,0
Exp/Cntr=0.3,0.1

Type RM Length L Ch R = 1 ,1098.9  ,165.6,167.6,168
XS GIS Cut Line= 2
     1669767.807      690620.464     1669937.946      690233.311
#Sta/Elev= 30
       0  757.97    29.5  756.12    88.5   752.8    98.4  752.35   108.2  752.07
   137.7  751.53   157.4  751.03     177  750.76   196.7  750.78   216.4  750.94
   245.9  751.43   255.7  751.23   265.5  750.01   275.4  747.64     284  745.76
   285.2   745.5     295  745.17     299  745.98   304.9  747.17   314.7  750.58
   324.5  754.34   334.4  758.41   344.2  763.25     354  769.32   363.9  776.17
   373.7  783.84   383.6  791.81   403.2  807.77     413  815.24   422.9  822.07
#Mann= 3 , 0 , 0
       0      .1       0     284    .045       0     299      .1       0
Bank Sta=284,299
XS Rating Curve= 0 ,0
Exp/Cntr=0.3,0.1

Type RM Length L Ch R = 1 ,931.3   ,120.9,119,116.4
XS GIS Cut Line= 3
     1669855.451      690788.953     1670048.594      690380.967
     1670042.083      690255.099
#Sta/Elev= 30
       0  796.51    19.6  786.63    29.4  781.27    39.2  775.68    49.1  770.59
    58.9  766.16    68.7  762.56    78.5  759.69    88.3  757.45    98.1  755.99
   117.8  754.39   147.2  752.55   166.8  751.56   196.3  750.26   225.7  749.21
   235.5  749.09   323.8  748.89   382.7  748.56   392.5  747.85   402.3   746.1
   412.5  744.44     422  744.28   427.5  745.49   431.8  746.43   441.6  750.39
   470.8  762.86     529  788.92   548.4  797.99     558   802.6   577.4  811.35
#Mann= 3 , 0 , 0
       0      .1       0   412.5    .045       0   427.5      .1       0
Bank Sta=412.5,427.5
XS Rating Curve= 0 ,0
Exp/Cntr=0.3,0.1

Type RM Length L Ch R = 1 ,812.3   ,179.4,170.1,160.4
XS GIS Cut Line= 3
     1669961.354      690931.314     1670169.688      690380.099
     1670150.156      690221.679
#Sta/Elev= 30
       0  843.89     9.8  837.77    19.6  830.73    49.1  807.26    68.8  793.79
    88.4  781.36    98.2  776.34     108  772.41   157.1  755.49     167  752.75
   176.8   751.2   235.7  747.16   255.4  746.39   343.7  745.32   412.5  745.16
   500.9  745.56   510.7  745.29   530.3  742.21   540.2  741.85   547.4  742.84
     550   743.2   569.6  748.87   579.4  751.33   589.3  752.78     608  754.64
   664.4  763.62   701.9  768.17   711.3  770.04   720.7  772.62   748.9  782.78
#Mann= 3 , 0 , 0
       0     .06       0   530.3    .045       0   547.4      .1       0
#XS Ineff= 2 , 0
          501.68  777.35
Permanent Ineff=
       F       F
Bank Sta=530.3,547.4
XS Rating Curve= 0 ,0
Exp/Cntr=0.3,0.1

Type RM Length L Ch R = 1 ,642.1   ,99.1,95.9,92.5
XS GIS Cut Line= 4
     1670280.365      691109.266     1670330.278       690861.87
     1670306.406      690304.144     1670241.302      690173.936
#Sta/Elev= 30
       0  822.71    19.4   813.5      68   791.4   106.8  769.85   126.2  760.97
   145.6  751.38   155.3  748.24   242.7  737.98   252.4  737.31   281.8  736.72
   330.7  737.29   409.1  740.51   448.2  741.08   565.8  741.23     605  741.75
   614.7  740.96   628.3   738.5   634.3  737.72   643.3  738.95   653.9  742.59
   663.7  746.44   673.5  748.73   683.3   749.4   693.1  749.53     791   749.8
   810.6  750.86   839.7  754.11   859.1  756.86   927.1   768.4   956.2  772.83
#Mann= 3 , 0 , 0
       0     .08       0   628.3    .045       0   643.3     .08       0
#XS Ineff= 2 , 0
          528.79  774.64
Permanent Ineff=
       F       F
Bank Sta=628.3,643.3
XS Rating Curve= 0 ,0
Exp/Cntr=0.3,0.1

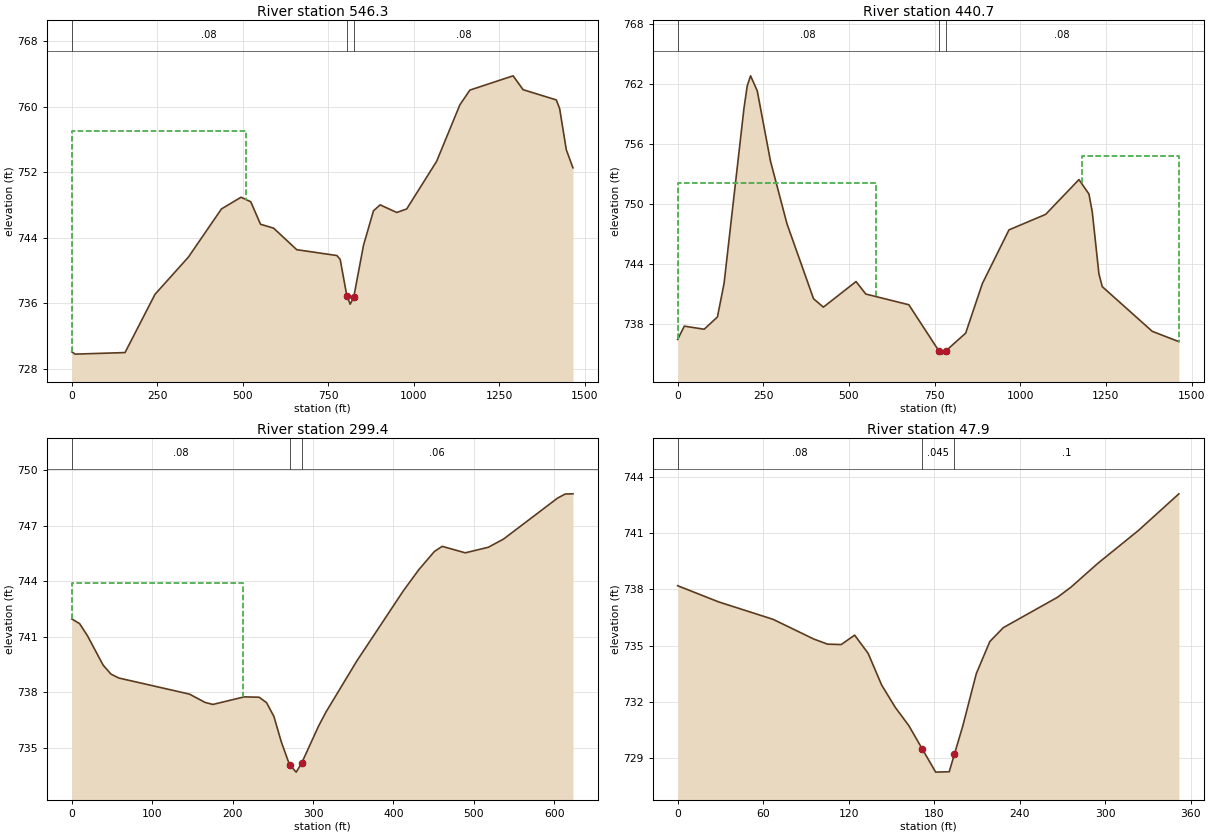
Type RM Length L Ch R = 1 ,546.3   ,107.4,105.5,105.6
XS GIS Cut Line= 5
     1670792.517      691198.241     1670562.483        690859.7
     1670466.997      690673.068     1670419.253      690534.179
     1670278.194      689848.415
#Sta/Elev= 30
       0   730.1     9.8  729.81   155.9     730   243.6  737.11   341.1  741.64
   437.9  747.52   495.1  748.95   523.6   748.4   552.2  745.65   590.4  745.18
   658.1  742.55   775.5  741.84   785.2  741.36   804.7   736.9   814.4   735.9
   824.8  736.76   853.3  743.08   882.5  747.29   901.9  748.02   950.6  747.09
   979.7  747.52  1067.2  753.33  1135.3  760.23  1164.5  762.02  1290.9  763.76
  1320.1  762.07  1417.3  760.82    1427  759.76  1446.5  754.74  1465.9  752.54
#Mann= 3 , 0 , 0
       0     .08       0   804.7    .045       0   824.8     .08       0
#XS Ineff= 2 , 0
          510.19  757.01
Permanent Ineff=
       F       F
Bank Sta=804.7,824.8
XS Rating Curve= 0 ,0
Exp/Cntr=0.3,0.1

Type RM Length L Ch R = 1 ,440.7   ,153.7,141.3,126.5
XS GIS Cut Line= 5
     1670883.663      691128.797     1670655.799      690792.425
     1670560.313      690605.794     1670512.569      690466.905
      1670371.51      689781.141
#Sta/Elev= 30
       0  736.42    19.4  737.75    77.4  737.44   116.1  738.67   135.4  742.02
   193.5  759.54   203.1   761.8   212.8  762.79   232.2   761.3   270.9  754.26
   319.2  747.97   396.6  740.49   425.3  739.65   520.6  742.21   549.2  740.96
   674.7  739.89   762.6  735.26   772.5  734.95   782.2  735.26   840.6  737.05
   889.2     742     967  747.38    1074  748.93  1171.2  752.41  1200.4  750.97
  1210.1  749.17  1229.5  742.98  1239.3   741.7  1385.1  737.23  1462.9   736.2
#Mann= 3 , 0 , 0
       0     .08       0   762.6    .045       0   782.2     .08       0
#XS Ineff= 2 , 0
          578.21  752.07  1179.1          754.74
Permanent Ineff=
       F       F
Bank Sta=762.6,782.2
XS Rating Curve= 0 ,0
Exp/Cntr=0.3,0.1

Type RM Length L Ch R = 1 ,299.4   ,265.5,251.5,235.2
XS GIS Cut Line= 5
     1670874.983      690436.523     1670662.309      690408.311
     1670586.354      690341.037     1670501.719      690223.849
     1670464.826      690065.429
#Sta/Elev= 30
       0  741.97     9.8  741.71    19.5  741.06      39  739.47    48.8  738.98
    58.5  738.77   146.3   737.9   165.8  737.45   175.5  737.34   214.5  737.75
     233  737.73   242.2  737.44   251.4  736.69   260.7   735.3   270.8  734.08
   279.1  733.68   285.8  734.16   306.8  736.16     316  736.92   354.6   739.7
   412.4  743.49   431.6  744.63   450.9  745.61   460.6  745.89   489.3  745.54
     518  745.84   537.1  746.29   604.1   748.5   613.6  748.72   623.2  748.73
#Mann= 3 , 0 , 0
       0     .08       0   270.8    .045       0   285.8     .06       0
#XS Ineff= 2 , 0
          213.29  743.92
Permanent Ineff=
       F       F
Bank Sta=270.8,285.8
XS Rating Curve= 0 ,0
Exp/Cntr=0.3,0.1

Type RM Length L Ch R = 1 ,47.9    ,55.5,47.9,40.3
XS GIS Cut Line= 3
     1670801.198      690254.231     1670770.816      690143.554
     1670534.271      690128.363
#Sta/Elev= 24
       0  738.19    28.7  737.33      67   736.4    95.6  735.35   105.2  735.08
   114.8  735.06   124.2  735.56   133.7  734.59   143.2   732.9   152.7  731.72
   162.2  730.75   171.7   729.5   181.1  728.27   190.6  728.29   194.3  729.24
   200.1  730.72   209.6  733.51   219.1  735.22   228.6  735.96   266.5  737.57
     276  738.11   294.9  739.38   323.4  741.13   351.8  743.08
#Mann= 3 , 0 , 0
       0     .08       0   171.7    .045       0   194.3      .1       0
Bank Sta=171.7,194.3
XS Rating Curve= 0 ,0
Exp/Cntr=0.3,0.1

Chan Stop Cuts=-1
Use User Specified Reach Order=0
Composite Channel Slope=5

--- SPNGTNSRN.g09 (geometry) ---

Geom Title=USGS 10m DEM
Program Version=4.10

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
River Reach=SPNGTNSRN       ,Main

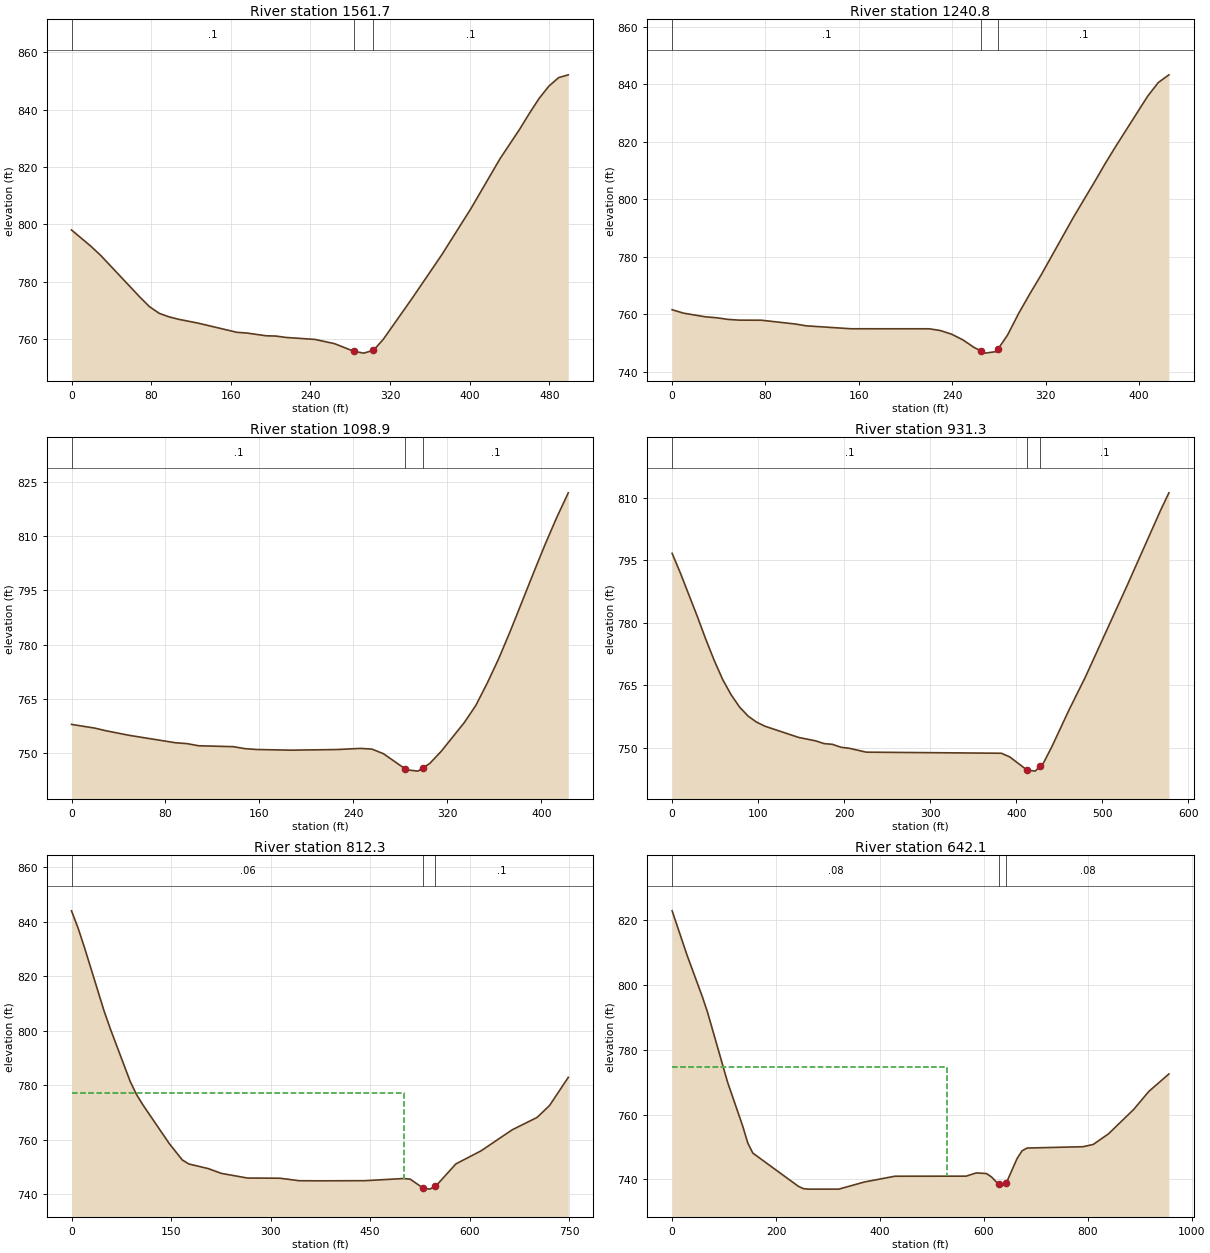
Type RM Length L Ch R = 1 ,1561.7  ,328.8,320.9,312
XS GIS Cut Line= 2
     1669288.611      690269.422     1669687.917      689969.943
#Sta/Elev= 30
       0  798.02    19.6   792.3    29.4  789.12    68.5  774.66    78.3  771.26
    88.1  768.92    97.9  767.69   107.7  766.83   127.2  765.49   166.4  762.27
   176.2  762.04   195.7  761.07   205.5  760.98   215.3   760.5   244.7   759.8
   264.2  758.33   283.8  755.64   293.6  755.02   303.4  756.02   313.2  759.81
   342.5  774.29   371.9  789.29   401.3  805.48   430.6  822.93   450.2  833.16
     460  838.71   469.8  843.94   479.6  848.23   489.4   851.2   499.1  852.18
#Mann= 3 , 0 , 0
       0      .1       0   283.8    .045       0   303.4      .1       0
Bank Sta=283.8,303.4
XS Rating Curve= 0 ,0
Exp/Cntr=0.3,0.1

Type RM Length L Ch R = 1 ,1240.8  ,144.8,141.9,138.4
XS GIS Cut Line= 3
     1669618.472      690521.158     1669792.083       690245.55
     1669837.656      690156.575
#Sta/Elev= 30
       0  761.62     9.6  760.44    28.7  759.14    38.3  758.82    47.9  758.26
    57.5     758    76.6  757.97   105.4  756.66     115  756.02   153.3     755
   220.4  754.99   229.9  754.38   239.5  753.11   249.1  751.16   258.7  748.52
   264.4  747.33   268.2  746.53   277.8  747.06   279.4  748.02   287.4  752.79
     297  760.38   306.6   767.2   316.2   773.7   343.9  793.78   362.1  806.15
   371.2  812.51   380.3  818.52   407.5  835.86   416.6  840.61   425.7  843.29
#Mann= 3 , 0 , 0
       0      .1       0   264.4    .045       0   279.4      .1       0
Bank Sta=264.4,279.4
XS Rating Curve= 0 ,0
Exp/Cntr=0.3,0.1

Type RM Length L Ch R = 1 ,1098.9  ,165.6,167.6,168
XS GIS Cut Line= 2
     1669767.807      690620.464     1669937.946      690233.311
#Sta/Elev= 30
       0  757.96    19.7  756.94    29.5  756.19    49.2  754.93    88.5  752.88
    98.4  752.64   108.2  752.05   137.7   751.8   147.5  751.26   157.4  751.02
   186.9  750.83   226.2  751.01   245.9  751.32   255.7  751.13   265.5  749.86
     284  745.68   285.2   745.4     295  745.04     299  745.89   304.9  747.14
   314.7   750.5   334.4  758.47   344.2   763.2     354  769.42   363.9  776.29
   373.7  783.86   393.4   799.9   403.2  807.72     413  815.09   422.9  821.96
#Mann= 3 , 0 , 0
       0      .1       0     284    .045       0     299      .1       0
Bank Sta=284,299
XS Rating Curve= 0 ,0
Exp/Cntr=0.3,0.1

Type RM Length L Ch R = 1 ,931.3   ,120.9,119,116.4
XS GIS Cut Line= 3
     1669855.451      690788.953     1670048.594      690380.967
     1670042.083      690255.099
#Sta/Elev= 30
       0  796.63     9.8  791.81    29.4  781.45    39.2  776.02    49.1   770.9
    58.9  766.36    68.7  762.73    78.5   759.8    88.3  757.67    98.1  756.23
   107.9  755.24   147.2  752.55   166.8  751.74   176.6  751.08   186.4   750.9
   196.3   750.2   206.1  749.95   225.7  749.03   382.7  748.77   392.5  747.88
   412.5  744.75     422  744.49   427.5  745.62   431.8  746.51   441.6  750.45
   461.1  759.05   480.5   767.1     529  789.01   567.7  806.93   577.4  811.12
#Mann= 3 , 0 , 0
       0      .1       0   412.5    .045       0   427.5      .1       0
Bank Sta=412.5,427.5
XS Rating Curve= 0 ,0
Exp/Cntr=0.3,0.1

Type RM Length L Ch R = 1 ,812.3   ,179.4,170.1,160.4
XS GIS Cut Line= 3
     1669961.354      690931.314     1670169.688      690380.099
     1670150.156      690221.679
#Sta/Elev= 30
       0  844.07     9.8  837.83    19.6  830.58    49.1  807.33    58.9  800.53
    88.4  781.52    98.2  776.58     108  772.74   147.3   758.7     167  752.66
   176.8  751.19   206.2  749.48   225.9  747.73   265.2  746.02   314.3  745.95
   343.7  745.03   373.2     745     442  745.05   500.9  745.84   510.7   745.6
   530.3  742.29   540.2  741.95   547.4  742.93     550  743.28   579.4  751.19
   617.4     756   664.4  763.72   701.9  768.26   720.7  772.64   748.9  782.96
#Mann= 3 , 0 , 0
       0     .06       0   530.3    .045       0   547.4      .1       0
#XS Ineff= 2 , 0
          501.68  777.35
Permanent Ineff=
       F       F
Bank Sta=530.3,547.4
XS Rating Curve= 0 ,0
Exp/Cntr=0.3,0.1

Type RM Length L Ch R = 1 ,642.1   ,99.1,95.9,92.5
XS GIS Cut Line= 4
     1670280.365      691109.266     1670330.278       690861.87
     1670306.406      690304.144     1670241.302      690173.936
#Sta/Elev= 30
       0  822.83    29.1  808.98    58.2  796.32      68  791.63   106.8  769.95
   135.9  756.42   145.6  751.22   155.3  748.12   242.7   737.9   252.4  737.16
   262.2     737   320.9     737   369.9  739.19   428.7  740.98   565.8     741
   585.4     742     605  741.81   614.7  740.76   628.3  738.49   634.3  737.93
   643.3  738.92   663.7  746.36   673.5  748.82   683.3  749.67     791  750.08
   810.6  750.79   839.7  754.02   888.3  761.56   917.4  767.11   956.2  772.52
#Mann= 3 , 0 , 0
       0     .08       0   628.3    .045       0   643.3     .08       0
#XS Ineff= 2 , 0
          528.79  774.64
Permanent Ineff=
       F       F
Bank Sta=628.3,643.3
XS Rating Curve= 0 ,0
Exp/Cntr=0.3,0.1

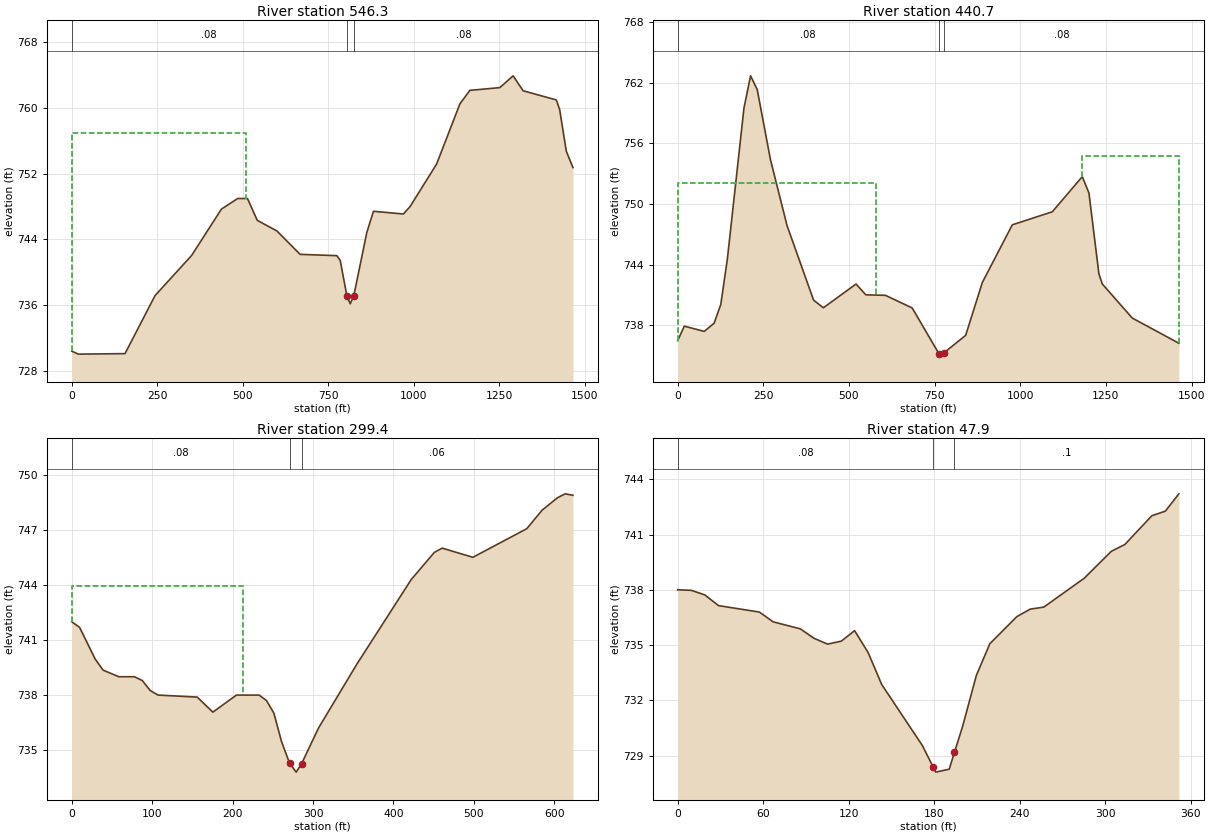
Type RM Length L Ch R = 1 ,546.3   ,107.4,105.5,105.6
XS GIS Cut Line= 5
     1670792.517      691198.241     1670562.483        690859.7
     1670466.997      690673.068     1670419.253      690534.179
     1670278.194      689848.415
#Sta/Elev= 30
       0  730.36    19.5     730   155.9  730.06   243.6  737.13   350.8  742.03
   437.9  747.68   485.5  748.97   514.1  748.96   542.7   746.3   599.9  745.02
   667.9  742.16   775.5     742   785.2  741.42   804.7  737.12   814.4  736.13
   824.8  737.08     863  744.82   882.5  747.41     970  747.08   989.5  747.98
  1067.2  753.17  1135.3   760.5  1164.5  762.15    1252  762.48  1290.9  763.92
  1320.1   762.1  1417.3  760.98    1427  759.82  1446.5  754.73  1465.9  752.74
#Mann= 3 , 0 , 0
       0     .08       0   804.7    .045       0   824.8     .08       0
#XS Ineff= 2 , 0
          510.19  757.01
Permanent Ineff=
       F       F
Bank Sta=804.7,824.8
XS Rating Curve= 0 ,0
Exp/Cntr=0.3,0.1

Type RM Length L Ch R = 1 ,440.7   ,153.7,141.3,126.5
XS GIS Cut Line= 5
     1670883.663      691128.797     1670655.799      690792.425
     1670560.313      690605.794     1670512.569      690466.905
      1670371.51      689781.141
#Sta/Elev= 30
       0  736.46    19.4   737.9    77.4  737.38   106.4  738.19   125.8  740.04
   145.1  744.55   193.5  759.49   212.8  762.68   232.2  761.32   270.9  754.37
   319.2  747.86   396.6  740.48   425.3  739.72   520.6  742.07   549.2     741
   606.4  740.95   684.5   739.7   762.6  735.17   772.5  735.13   777.6  735.27
   840.6  736.99   889.2  742.22   976.7  747.93  1093.4  749.22  1180.9   752.7
  1200.4  751.08  1229.5  743.07  1239.3  742.08  1326.8   738.7  1462.9  736.21
#Mann= 3 , 0 , 0
       0     .08       0   762.6    .045       0   777.6     .08       0
#XS Ineff= 2 , 0
          578.21  752.07  1179.1          754.74
Permanent Ineff=
       F       F
Bank Sta=762.6,777.6
XS Rating Curve= 0 ,0
Exp/Cntr=0.3,0.1

Type RM Length L Ch R = 1 ,299.4   ,265.5,251.5,235.2
XS GIS Cut Line= 5
     1670874.983      690436.523     1670662.309      690408.311
     1670586.354      690341.037     1670501.719      690223.849
     1670464.826      690065.429
#Sta/Elev= 30
       0     742     9.8  741.69    29.2  739.96      39  739.36    58.5     739
      78     739    87.8  738.79    97.5  738.25   107.3     738     156  737.89
   175.5  737.07   204.8     738     233     738   242.2   737.7   251.4  737.01
   260.7  735.49   270.8  734.29   279.1   733.8   285.8  734.26   306.8   736.2
   354.6  739.69     422  744.29   450.9  745.78   460.6  746.01   498.8  745.51
   565.8  747.07   584.9  748.08   604.1  748.76   613.6  748.97   623.2  748.89
#Mann= 3 , 0 , 0
       0     .08       0   270.8    .045       0   285.8     .06       0
#XS Ineff= 2 , 0
          213.29  743.92
Permanent Ineff=
       F       F
Bank Sta=270.8,285.8
XS Rating Curve= 0 ,0
Exp/Cntr=0.3,0.1

Type RM Length L Ch R = 1 ,47.9    ,55.5,47.9,40.3
XS GIS Cut Line= 3
     1670801.198      690254.231     1670770.816      690143.554
     1670534.271      690128.363
#Sta/Elev= 30
       0     738     9.6  737.97    19.1  737.72    28.7  737.14    57.4  736.79
      67  736.26    86.1  735.88    95.6  735.37   105.2  735.05   114.8  735.21
   124.2  735.78   133.7  734.59   143.2  732.86   171.7  729.55   179.3  728.38
   181.1   728.1   190.6  728.26   194.3  729.18   200.1  730.61   209.6  733.34
   219.1  735.07     238  736.54   247.5  736.95     257  737.06   285.4  738.63
   304.4  740.09   313.9  740.46   332.8  742.02   342.3  742.27   351.8  743.21
#Mann= 3 , 0 , 0
       0     .08       0   179.3    .045       0   194.3      .1       0
Bank Sta=179.3,194.3
XS Rating Curve= 0 ,0
Exp/Cntr=0.3,0.1